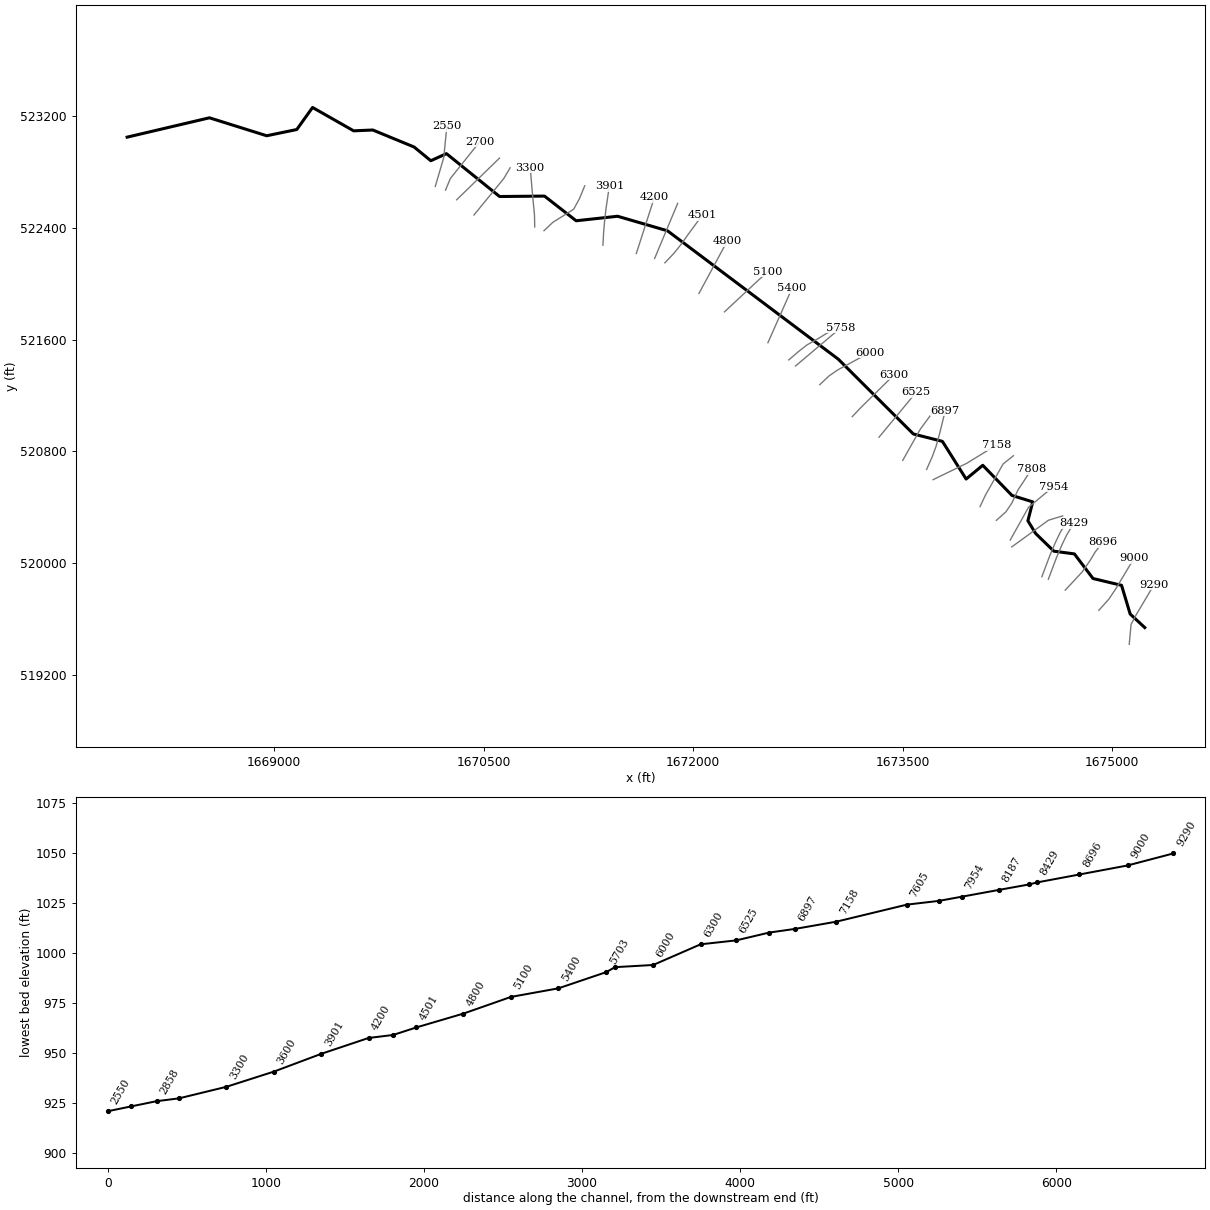
--- GrannyRn.prj (project) ---

Proj Title=GrannyRn
Current Plan=p01
Default Exp/Contr=0,0
English Units
Geom File=g01
Flow File=f01
Plan File=p01
BEGIN DESCRIPTION:
---------- MODELED AS PART OF WVEM CTP PROGRAM, 2025----------
Stream Name: Granny Run
Flood Zone: AFH
Marshall County, WV
HEC-RAS Version: RAS 6.6
Vertical Datum: NAVD88
Projection: NAD 1983 StatePlane West Virginia N FIPS 4701 (US Feet)
Terrain: 1-meter West Virginia FEMA R3 South Central (collected 2018-2019)
Land Use: 2024 NLCD
Hydrologic Method:
Duda et al., "Estimation of magnitude and frequency of floods for rural, unregulated streams in and near Virginia and West Virginia." September 8, 2025.
Additional Model Notes:
None
END DESCRIPTION:
DSS Export Rating Curves= 0
DSS Export Rating Curve Sorted= 0
DSS Export Volume Flow Curves= 0
DXF OffsetX= 0
DXF OffsetY= 0
DXF ScaleX= 0
DXF ScaleY= 0

--- GrannyRn.p01 (plan) ---

Plan Title=Floodplain
Program Version=6.60
Short Identifier=Floodplain
Geom File=g01
Flow File=f01
Subcritical Flow
K Sum by GR= 0
Std Step Tol= 0.01
Critical Tol= 0.01
Num of Std Step Trials= 20
Max Error Tol= 0.3
Flow Tol Ratio= 0.001
Split Flow NTrial= 30
Split Flow Tol= 0.02
Split Flow Ratio= 0.02
Log Output Level= 0
Friction Slope Method= 1
Unsteady Friction Slope Method= 2
Unsteady Bridges Friction Slope Method= 1
Parabolic Critical Depth
Global Vel Dist= 0 , 0 , 0
Global Log Level= 0
CheckData=False
Encroach Param=-1 ,0,0, 0
Flow Ratio Tolerance=0.1
Flow Ratio Min Ratio=0.5
Flow Ratio Max Ratio=4
Flow Ratio Max Iterations= 10
Mapping Interval=1HOUR
Computation Time Step Use Courant=        0
Computation Time Step Use Time Series=    0
Computation Time Step Count To Double=0
Computation Time Step Max Doubling=0
Computation Time Step Max Halving=0
Computation Time Step Residence Courant=0
Run HTab= 0
Run UNet= 0
Run Sediment= 0
Run PostProcess= 0
Run WQNet= 0
Run RASMapper=-1
UNET Theta= 0
UNET Theta Warmup= 0
UNET ZTol= 0
UNET ZSATol= 0
UNET MxIter= 0
UNET Max Iter WO Improvement= 0
UNET MaxInSteps= 0
UNET DtIC= 0
UNET DtMin= 0
UNET MaxCRTS= 0
UNET WFStab= 0
UNET SFStab= 0
UNET WFX= 1
UNET SFX= 1
UNET Gravity=32.17405
UNET 1D Methodology=Finite Difference
UNET DSS MLevel= 1
UNET Pardiso=0
UNET DZMax Abort= 0
UNET Use Existing IB Tables= 0
UNET Froude Reduction=False
UNET Froude Limit= 0
UNET Froude Power= 0
UNET D1 Cores= 0
UNET WindReference=Eulerian
UNET WindDragFormulation=Hsu (1988)
UNET D2 Coriolis=0
UNET D2 Cores= 0
UNET D2 Theta= 1
UNET D2 Theta Warmup= 1
UNET D2 Z Tol= 0.01
UNET D2 Volume Tol= 0.01
UNET D2 Max Iterations= 20
UNET D2 Advanced Convergence=0
UNET D2 WS Max Tol=0.15
UNET D2 WS RMS Tol=0.002
UNET D2 WS Stall Tol=1
UNET D2 Equation= 0
UNET D2 RampUpFraction=0.1
UNET D2 TimeSlices= 1
UNET D2 Turbulence Formulation=Non-Conservative (original)
UNET D2 Eddy Viscosity=0.3
UNET D2 Transverse Eddy Viscosity=0.1
UNET D2 Smagorinsky Mixing=0
UNET D2 BCVolumeCheck=0
UNET D2 Cores=0
UNET D2 SolverType=PARDISO (Direct)
UNET D2 Minimum Iterations= 3
UNET D2 Maximum Iterations= 30
UNET D2 Restart Number= 10
UNET D2 Relaxation Coeff=1.3
UNET D2 SOR Precondition Iterations= 10
UNET D2 ILUT Maximum Fill= 8
UNET D2 ILUT Tolerance=1E-08
UNET D2 Convergence Tolerance=0.00001
PS Theta= 1
PS WS Tol= 0.01
PS Volume Tol= 0.01
PS Max Iterations= 20
PS Equation= 0
PS Advance Time Step=-1
PS Target Courant=0.9
PS Time Slices= 1
PS Iterate With 2D=0
PS Project Initial WSE from DS=-1
PS Ramp Up Initial WSE from US=-1
PS Cores=0
UNET D1D2 MaxIter= 0
UNET D1D2 ZTol=0.01
UNET D1D2 QTol=0.1
UNET D1D2 MinQTol=1
Write IC File= 0
Write IC File at Fixed DateTime=0
Write IC File at Sim End=0
Echo Input=False
Echo Parameters=False
Echo Output=False
Write Detailed= 0
HDF Write Warmup=0
HDF Write Time Slices=0
HDF Flush=0
HDF Compression= 1
HDF Chunk Size= 1
HDF Spatial Parts= 1
HDF Use Max Rows=0
HDF Fixed Rows= 1
Calibration Method= 0
Calibration Iterations= 20
Calibration Max Change=0.05
Calibration Tolerance=0.2
Calibration Maximum=1.5
Calibration Minimum=0.5
Calibration Optimization Method= 1
WQ AD Non Conservative
WQ ULTIMATE=-1
WQ Max Comp Step=1HOUR
WQ Output Interval=15MIN
WQ Output Selected Increments= 0
WQ Create Restart=0
WQ Fixed Restart=0
WQ System Summary=0
WQ Write To DSS=0
Sorting and Armoring Iterations= 10
XS Update Threshold= 0.02
Bed Roughness Predictor= 0
Processes Affected by Predictor=Sediment Only
Hydraulics Update Threshold= 0.02
Energy Slope Method= 1
Volume Change Method= 1
Sediment Retention Method= 0
Sediment TS Multiplier= 1
Warm Up Method= 0
XS Weighting Method= 0
Number of US Weighted Cross Sections= 1
Number of DS Weighted Cross Sections= 1
Upstream XS Weight=0
Main XS Weight=1
Downstream XS Weight=0
Number of DS XS's Weighted with US Boundary= 1
Upstream Boundary Weight= 1
Weight of XSs Associated with US Boundary= 0
Number of US XS's Weighted with DS Boundary= 1
Downstream Boundary Weight= 0.5
Weight of XSs Associated with DS Boundary= 0.5
Percentile Method= 0
Sediment Output Level= 3
Mass or Volume Output= 0
Output Increment Type= 1
Profile and TS Output Increment= 1
Transport Output Increment 1
XS Output Flag= 0
XS Output Increment= 10
Read HDF5 Sediment Hotstart= 0
Sediment Hotstart Type= 0
Write Gradation File= 0
Read Gradation Hotstart= 0
Write HDF5 File= 1
Write Binary Output= 1
Write DSS Sediment File= 0
DSS Sediment Output Type= 1
SV Curve= 0
Specific Gage Flag= 0
Subcell Erosion Methods= 0
Subcell Deposition Methods= 0
Advection Scheme= 1
Matrix Solver= 0
Implicit Weighting Factor= 1
Maximum Outer Loop Convergence Iterations= 5
Convergence Maximum Absolute= 0.001
Convergence RMSE= 0.0001
Grain Fractions Max Abs Error= 0.001
Max Subgrid Regions= 1
Max Subgrid Length Scale= 3.402823E+38
Initial Layer Thickness= 3
Min Layer Thickness= 0.1
Max Layer Thickness= 6
Number of Layers= 5

--- GrannyRn.f01 (steady flow) ---

Flow Title=Flow
Program Version=6.60
Number of Profiles= 1
Profile Names=P100yr
River Rch & RM=GrannyRn,Main,9290
     750
River Rch & RM=GrannyRn,Main,7158
     961
River Rch & RM=GrannyRn,Main,4200
    1100
River Rch & RM=GrannyRn,Main,1800
    1270
Boundary for River Rch & Prof#=GrannyRn,Main            , 1
Up Type= 0
Dn Type= 3
Dn Slope=0.02916
DSS Import GetInterval= 0
DSS Import GetPeak= 0
DSS Import FillOption= 0

--- GrannyRn.g01 (geometry) ---

Geom Title=Geometry
Program Version=6.60

River Reach=GrannyRn        ,Main
Reach XY= 30
      1675234.18      519538.749     1675129.681      519635.527
     1675067.908      519840.922     1674863.543      519889.825
     1674730.216      520065.878     1674582.991      520085.439
     1674452.447      520212.508      1674397.35      520302.996
     1674432.162      520438.317     1674283.413      520484.286
     1674074.137       520700.08     1673954.967      520601.758
     1673785.277      520871.233     1673577.122      520924.264
     1673039.634      521459.629     1671816.661      522378.457
     1671459.266      522482.533     1671162.746      522450.132
     1670935.938      522626.865     1670614.504      522623.736
     1670234.036      522930.565     1670122.043      522879.938
      1670002.38      522978.124     1669706.796      523099.798
     1669569.618      523093.779     1669275.271      523261.138
     1669162.519       523103.33     1668946.913      523058.645
     1668536.925      523187.115     1667947.662      523048.607

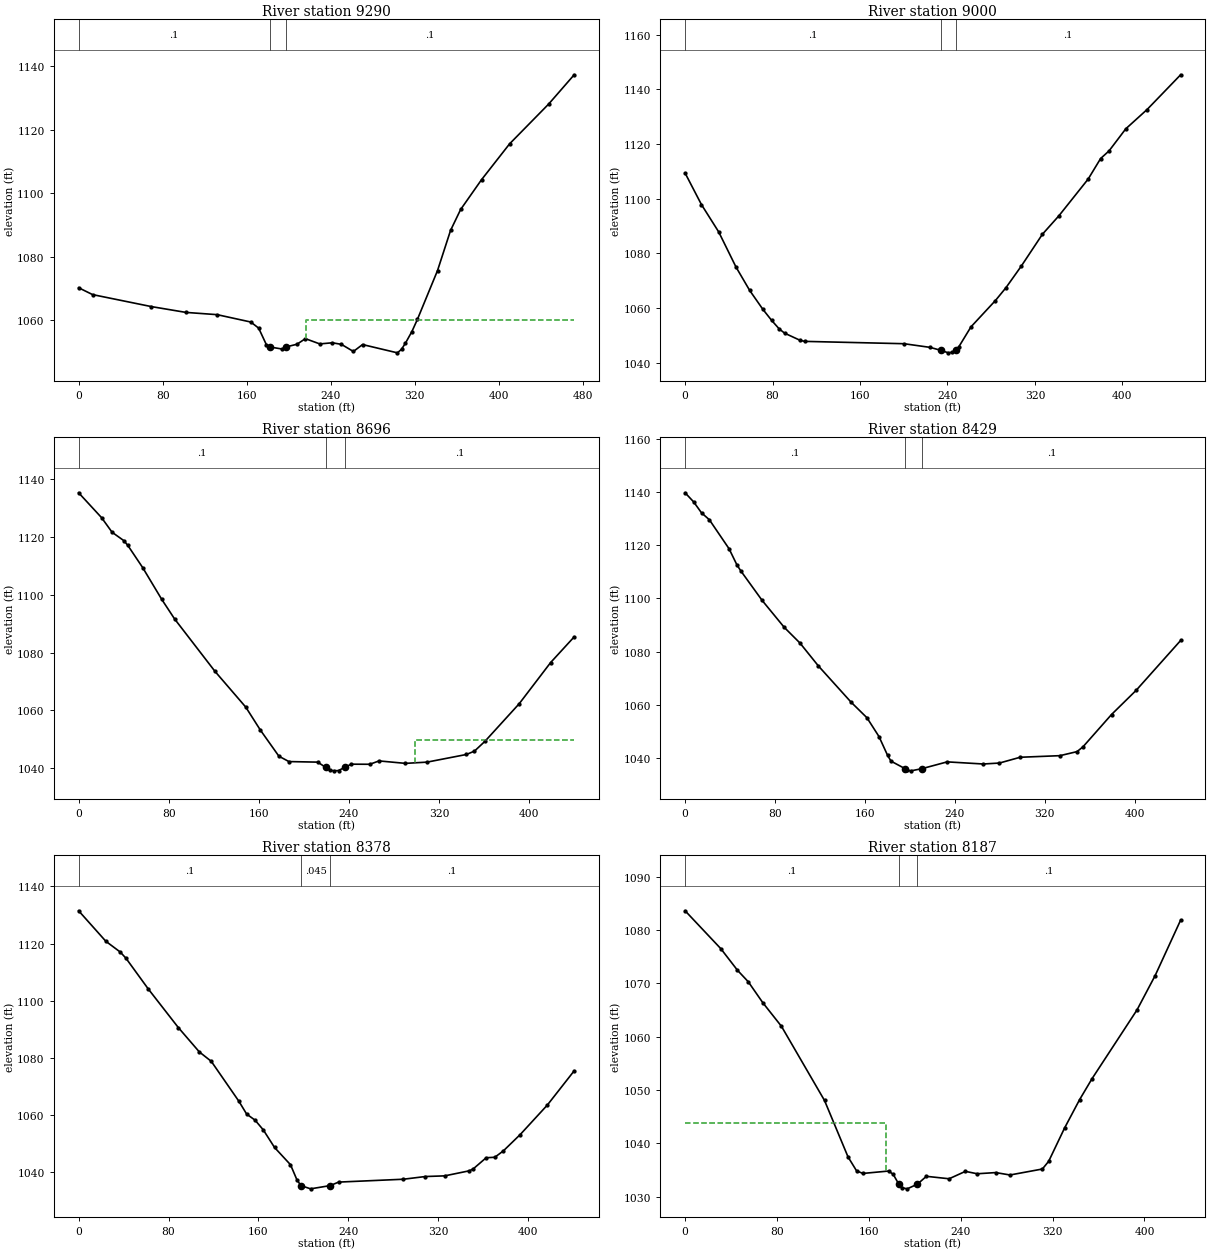
Type RM Length L Ch R = 1 ,9290    ,292.3,290.4,290.9
XS GIS Cut Line= 4
1675122.97999742519419.2964525751675136.21225943519561.414258748
1675171.67054167519628.3267765961675300.77058753519846.256711334
#Sta/Elev= 30
       0 1070.16    13.3    1068    69.3 1064.22   102.2 1062.39   131.9 1061.68
   163.9 1059.36   171.4 1057.44   178.8 1052.18  182.011051.495   193.6 1050.86
   197.3  1051.5   207.9 1052.36   215.9 1054.12   229.6 1052.46   241.6 1052.82
   250.2 1052.32   261.6 1050.08   270.3 1052.26   303.5 1049.65   307.4 1050.76
   311.2 1052.73   317.3 1056.36   322.6 1060.23   341.7 1075.58   354.1 1088.22
   363.7 1094.82   383.6 1104.21   410.3  1115.5   447.5 1128.04   471.8 1137.27
#Mann= 3, -1 ,  0
       0     0.1       0  182.01   0.045       0   197.3     0.1       0
#XS Ineff= 2 , 0
                          216.61         1059.97
Permanent Ineff=
       F       F
Bank Sta=182.01,197.3
XS Rating Curve= 0 ,0
Exp/Cntr(USF)=0,0
Exp/Cntr=0.3,0.1

Type RM Length L Ch R = 1 ,9000    ,303.1,303.8,301.5
XS GIS Cut Line= 6
1674905.59198576519662.1889915911674976.94978267519742.238700256
1675023.75185442519811.5253070891675075.20417935 519897.27283901
1675113.79071634519961.5853744151675158.80801475520036.616392344
#Sta/Elev= 30
       0 1109.37      15 1097.82    30.7 1087.88    46.6 1074.98    59.1 1066.44
    71.2 1059.51    79.1 1055.53      86 1052.42      91 1050.83   105.4 1048.17
   109.6 1047.82   200.2 1046.97   224.1 1045.63  233.761044.567   240.8 1043.63
   244.6 1043.86  247.511044.568   250.1 1045.65   261.5 1053.13   283.9 1062.77
   293.5 1067.45   307.4 1075.27   326.9 1087.02   341.9 1093.73   368.7 1107.18
   380.1 1114.69   387.8 1117.48   403.1 1125.55   422.6 1132.61   453.3 1145.32
#Mann= 3, -1 ,  0
       0     0.1       0  233.76   0.045       0  247.51     0.1       0
Bank Sta=233.76,247.51
XS Rating Curve= 0 ,0
Exp/Cntr(USF)=0,0
Exp/Cntr=0.3,0.1

Type RM Length L Ch R = 1 ,8696    ,262.4,267.7,264.6
XS GIS Cut Line= 6
1674664.69056468519806.7395555081674728.49850792519874.645587668
1674784.19590309 519934.890545921674842.12754576520017.862164751
1674880.81185159520082.1182698461674936.59750117520150.729681179
#Sta/Elev= 30
       0 1135.22    20.4 1126.61    29.7 1121.58    40.2 1118.66    43.7 1117.01
    56.9 1109.34    73.8 1098.37    85.2 1091.62     121 1073.53   148.4 1061.14
   161.2  1053.3   177.8 1044.19   186.7 1042.34   212.2 1042.15  219.341040.338
   222.7 1039.39   226.7 1039.14   230.7 1039.24  236.17 1040.34     242 1041.44
   258.5 1041.41   266.7 1042.57   290.1 1041.72   309.3 1042.15   344.3  1044.8
   351.4 1045.96   360.8 1049.38   391.1 1062.33     419 1076.56   439.9 1085.43
#Mann= 3, -1 ,  0
       0     0.1       0  219.34   0.045       0  236.17     0.1       0
#XS Ineff= 2 , 0
                          298.92         1049.66
Permanent Ineff=
       F       F
Bank Sta=219.34,236.17
XS Rating Curve= 0 ,0
Exp/Cntr(USF)=0,0
Exp/Cntr=0.3,0.1

Type RM Length L Ch R = 1 ,8429    ,50.3,50.6,52
XS GIS Cut Line= 6
1674543.72001708519884.7271063561674574.57330182 519966.60686385
1674601.01911508 520036.789794351674640.58104383520129.320449182
1674674.48845633520200.4633515271674725.51558525520285.212197775
#Sta/Elev= 30
       0 1139.66     7.6 1136.24    14.6 1132.13    21.6 1129.52    39.1 1118.64
    46.1 1112.57    49.6 1110.29    68.5 1099.24    88.2  1089.1   102.2  1083.2
   118.6 1074.59   147.8 1060.93   161.8 1055.13   172.5 1048.07   180.2 1040.96
   183.2 1038.82  195.611036.024   197.5 1035.35   201.1 1035.18  210.961036.023
   233.2 1038.55   265.3 1037.75   279.7 1038.11   298.1 1040.28   333.5 1040.88
   348.7  1042.4     354  1044.2   379.4 1056.34   401.3 1065.42   440.9 1084.16
#Mann= 3, -1 ,  0
       0     0.1       0  195.61   0.045       0  210.96     0.1       0
Bank Sta=195.61,210.96
XS Rating Curve= 0 ,0
Exp/Cntr(USF)=0,0
Exp/Cntr=0.3,0.1

Type RM Length L Ch R = 1 ,8378    ,194.8,191.1,182.6
XS GIS Cut Line= 6
1674497.39356609519902.8277283571674528.24685083519984.707485851
1674554.69266409520054.8904163511674594.25459284520147.421071183
1674628.16200534520218.5639735281674679.18913426520303.312819775
#Sta/Elev= 30
       0 1131.48    24.2 1120.81      37 1117.05    42.1 1114.88    61.9 1104.15
    88.7 1090.61   107.4 1082.08     118  1078.8   142.5 1064.87   149.5 1060.33
     157  1058.2   164.3  1054.8   174.3 1048.65   188.5 1042.61   194.2 1037.35
  197.761035.309   206.4 1034.17  223.821035.308   231.3 1036.53   288.9 1037.53
   308.5 1038.48   325.7 1038.71   347.7 1040.49   351.2 1041.19   362.6 1045.05
   370.3 1045.22     378 1047.49   392.9 1053.17     417 1063.48   440.9 1075.47
#Mann= 3, -1 ,  0
       0     0.1       0  197.76   0.045       0  223.82     0.1       0
Bank Sta=197.76,223.82
XS Rating Curve= 0 ,0
Exp/Cntr(USF)=0,0
Exp/Cntr=0.3,0.1

Type RM Length L Ch R = 1 ,8187    ,225.5,232.8,225.5
XS GIS Cut Line= 3
1674281.49509552  520115.70156981674544.28988685520306.842886001
1674646.16862009520337.982915595
#Sta/Elev= 30
       0 1083.62    31.1 1076.51    45.6 1072.46      55  1070.3    67.7 1066.36
    83.9 1061.94   121.4 1048.02   141.9 1037.42   149.3 1034.82   154.8 1034.33
   177.2 1034.78   181.2 1034.17  186.08 1032.32   188.9 1031.65   193.4 1031.44
  202.311032.319   210.1 1033.79   229.9 1033.33   244.1 1034.72   254.3 1034.27
   270.5 1034.49   282.9 1034.04   311.1 1035.16   316.6 1036.61   330.4 1042.84
   343.5 1048.17   354.4 1052.13   393.5 1065.01   409.3 1071.46   431.5 1081.87
#Mann= 3, -1 ,  0
       0     0.1       0  186.08   0.045       0  202.31     0.1       0
#XS Ineff= 2 , 0
          174.97 1043.72
Permanent Ineff=
       F       F
Bank Sta=186.08,202.31
XS Rating Curve= 0 ,0
Exp/Cntr(USF)=0,0
Exp/Cntr=0.3,0.1

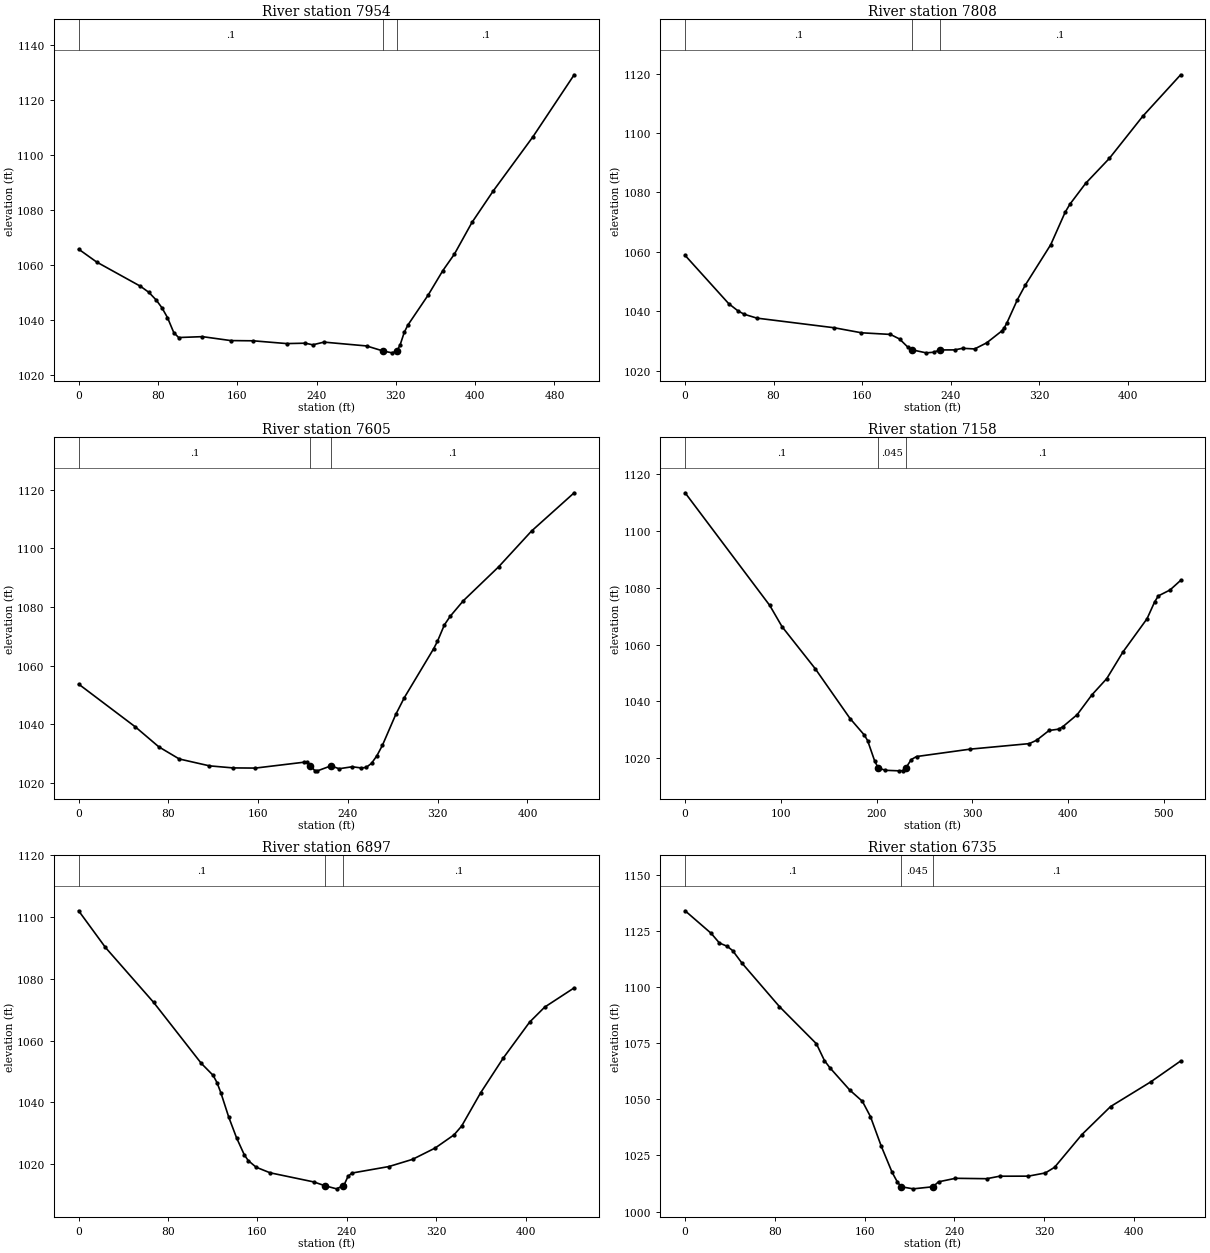
Type RM Length L Ch R = 1 ,7954    ,141.4,146.3,146.2
XS GIS Cut Line= 3
1674270.59300029520164.6865236071674401.75546996520399.186581204
1674579.51623556520547.027217945
#Sta/Elev= 30
       0 1065.81    18.2 1061.12    62.3 1052.32    70.8 1050.11    78.3 1047.28
      84  1044.5    89.6 1040.93      96 1035.44   100.9 1033.65   124.9 1033.97
   153.5 1032.54     176 1032.46   209.9 1031.45   228.6 1031.59   236.2    1031
   247.5 1031.98   290.5 1030.59   307.2 1028.74   316.2 1028.08  321.01 1028.74
   324.3 1030.94   328.5 1035.55   332.1 1038.16   352.6  1049.1   367.4    1058
   379.1 1064.02   396.8 1075.53   418.1 1086.91   458.3  1106.7   499.9 1129.26
#Mann= 3, -1 ,  0
       0     0.1       0   307.2   0.045       0  321.01     0.1       0
Bank Sta=307.2,321.01
XS Rating Curve= 0 ,0
Exp/Cntr(USF)=0,0
Exp/Cntr=0.3,0.1

Type RM Length L Ch R = 1 ,7808    ,204.2,203,200.8
XS GIS Cut Line= 6
1674171.58689208520305.9636226741674240.08773933520367.296177179
1674282.80090851520430.8393571671674326.73126684520524.373947009
1674372.48281576520593.2104234991674422.65528759520672.028835416
#Sta/Elev= 30
       0 1058.78    39.4 1042.53      48 1040.03    53.6 1038.93    64.9 1037.65
   134.9  1034.4   159.4 1032.71   185.6 1032.16   193.8 1030.63   201.5 1027.82
   205.5 1026.95   217.8 1025.96   224.7 1026.16   230.1 1026.94   243.6 1026.95
   250.8 1027.49   261.7 1027.27   272.6 1029.33   286.2 1033.31   288.4 1034.32
     291 1036.15   300.4 1043.89   307.5 1048.78   330.5 1062.39   343.5 1073.29
   347.8    1076     362 1083.02   383.4 1091.41   413.7 1105.64   447.9 1119.59
#Mann= 3, -1 ,  0
       0     0.1       0   205.5   0.045       0   230.1     0.1       0
Bank Sta=205.5,230.1
XS Rating Curve= 0 ,0
Exp/Cntr(USF)=0,0
Exp/Cntr=0.3,0.1

Type RM Length L Ch R = 1 ,7605    ,450.9,446.5,429.4
XS GIS Cut Line= 4
1674054.82400225520404.4411160051674093.37067941520486.798521269
1674220.20949826 520709.959533841674293.74445617520768.434154421
#Sta/Elev= 30
       0 1053.67    50.6 1039.06    71.5 1032.26    89.7 1028.13   116.6 1025.79
   137.5 1025.09   157.5 1025.03   200.8 1027.03   203.2 1026.95   206.6 1025.82
   210.4 1024.19   212.8 1024.09   224.9 1025.79   232.1 1024.81   243.8 1025.48
   251.9 1025.07   256.2 1025.25     261 1026.65   265.8 1029.24   270.7 1032.78
   282.6 1043.31   290.2 1049.02   316.3 1065.68   319.8 1068.28   325.9 1073.82
   331.1 1076.78   342.8 1082.08   374.3 1093.66   403.6 1105.85   441.6  1118.9
#Mann= 3, -1 ,  0
       0     0.1       0   206.6   0.045       0   224.9     0.1       0
Bank Sta=206.6,224.9
XS Rating Curve= 0 ,0
Exp/Cntr(USF)=0,0
Exp/Cntr=0.3,0.1

Type RM Length L Ch R = 1 ,7158    ,249.4,260.8,266.6
XS GIS Cut Line= 3
1673718.58102913520597.1299026311673960.26087117520714.796794504
1674172.34524549520845.247007187
#Sta/Elev= 30
       0 1113.44    88.5 1073.77   101.3 1066.32   135.9 1051.56   172.4 1033.98
   187.2 1028.21   190.7 1026.24     198 1019.14  201.751016.605   209.3 1015.77
   223.5 1015.58   227.2 1015.66  230.681016.606   236.3 1019.55   241.8 1020.61
     298 1023.22   359.7 1025.16   367.4 1026.37   380.3 1029.78   390.5 1030.26
   394.6 1031.09   409.7 1035.35   425.1 1042.33   440.6 1048.04   457.6 1057.45
   482.7 1069.12   490.6 1075.01   494.5 1077.15   506.7 1079.23   517.8 1082.61
#Mann= 3, -1 ,  0
       0     0.1       0  201.75   0.045       0  230.68     0.1       0
Bank Sta=201.75,230.68
XS Rating Curve= 0 ,0
Exp/Cntr(USF)=0,0
Exp/Cntr=0.3,0.1

Type RM Length L Ch R = 1 ,6897    ,163.7,162.8,155.2
XS GIS Cut Line= 6
1673672.01210384520670.4146654161673711.50743167520759.164816007
1673740.33512992520837.3657750931673767.05620509520934.181854427
1673784.90000142521007.0265250061673805.71623276521092.001420677
#Sta/Elev= 30
       0 1102.08      24 1090.19    67.1  1072.4   109.8 1052.62   120.3 1048.77
   123.8 1046.41   127.3 1043.08   134.3 1035.23   141.3 1028.52   148.3 1022.95
   151.8 1021.13   158.8 1018.99   171.3 1017.18   210.4 1014.22   220.41012.981
   230.8 1011.98  236.491012.981   237.6 1013.31     241    1016   244.5 1017.09
   277.6  1019.2   298.8 1021.54     319  1025.2   335.9 1029.47   342.7 1032.31
   359.6 1043.04   379.8 1054.28   403.5 1065.99     417 1070.86   443.4  1077.1
#Mann= 3, -1 ,  0
       0     0.1       0   220.4   0.045       0  236.49     0.1       0
Bank Sta=220.4,236.49
XS Rating Curve= 0 ,0
Exp/Cntr(USF)=0,0
Exp/Cntr=0.3,0.1

Type RM Length L Ch R = 1 ,6735    ,207.8,209.8,202.2
XS GIS Cut Line= 3
1673500.98387907520734.8819436391673626.84453543520958.498449599
1673736.81986623 521107.57612024
#Sta/Elev= 30
       0 1133.92    23.2  1123.9    30.6 1119.58    37.6  1118.1    42.4 1116.19
    50.7 1110.64    84.1 1091.29   117.1 1074.73   124.3 1067.22   129.1 1064.06
   146.9 1054.09   158.1 1049.12   165.3  1042.3   174.9 1029.19   184.6 1017.51
   189.4 1013.11  192.74 1011.08   203.4 1010.16  220.95 1011.08     226 1013.28
   241.1 1014.85   268.9 1014.67   280.5 1015.78   306.1 1015.81   321.3 1017.24
   329.5 1019.76   353.9 1034.34   379.4 1046.78   415.1 1057.72   441.9 1067.06
#Mann= 3, -1 ,  0
       0     0.1       0  192.74   0.045       0  220.95     0.1       0
Bank Sta=192.74,220.95
XS Rating Curve= 0 ,0
Exp/Cntr(USF)=0,0
Exp/Cntr=0.3,0.1

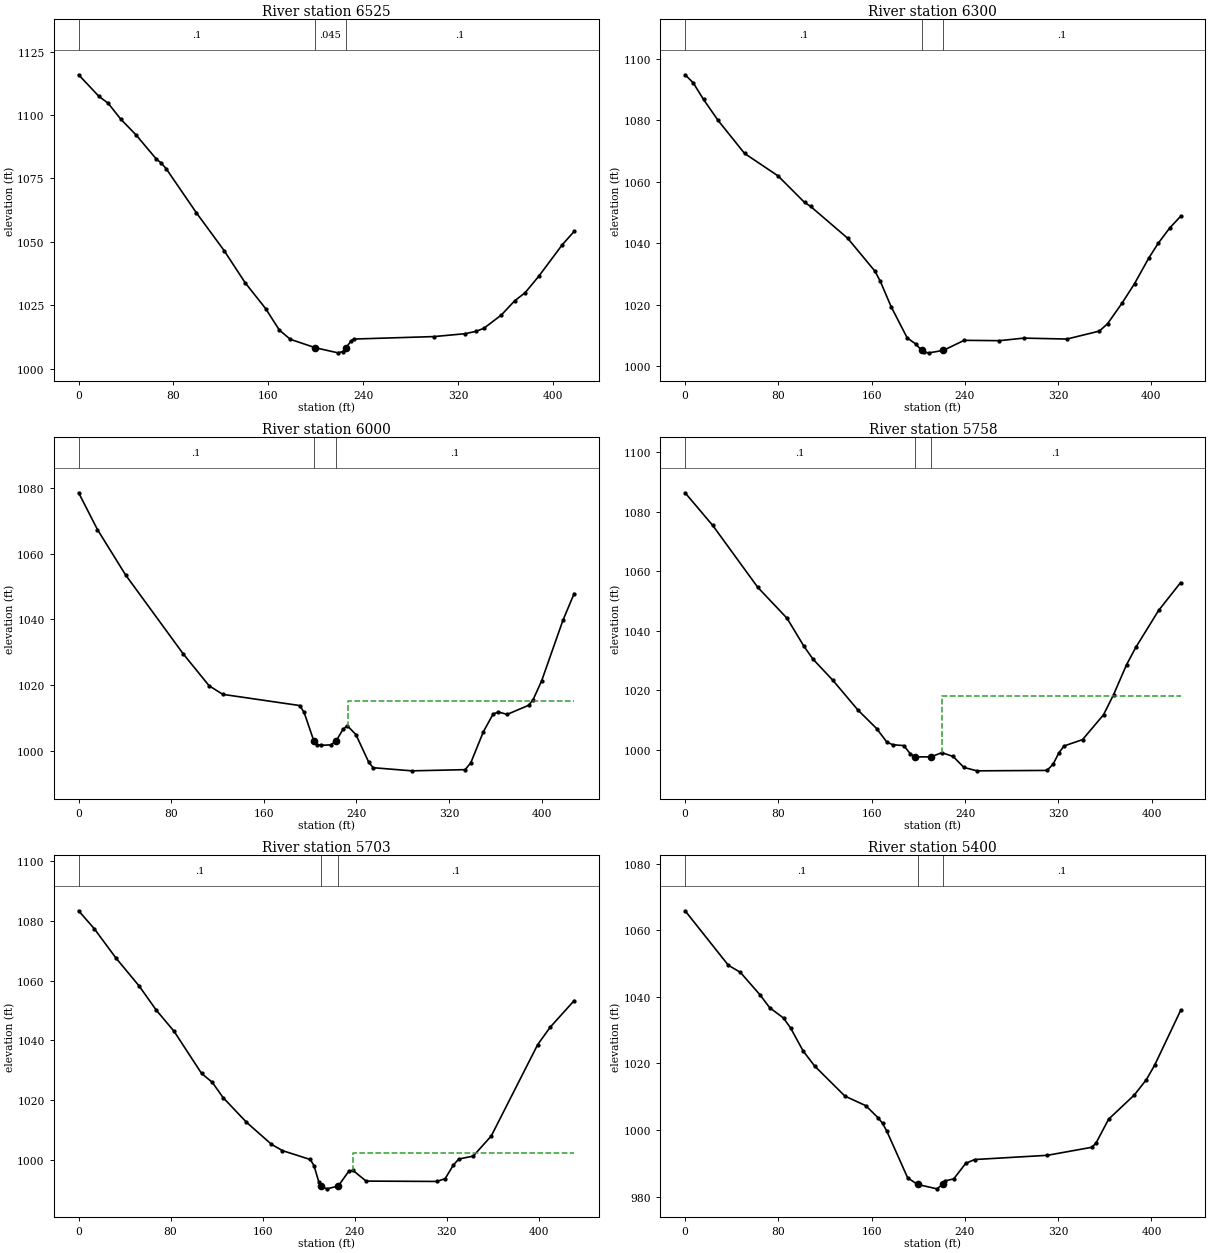
Type RM Length L Ch R = 1 ,6525    ,225.1,224.9,223.7
XS GIS Cut Line= 2
1673331.27229975520901.1254900841673597.85918811521223.143074797
#Sta/Elev= 30
       0 1115.88      17 1107.42    24.9 1104.66    35.6 1098.35    48.4 1092.18
    65.4 1082.73    69.7 1081.09    73.8 1078.88    99.3 1061.48   122.7 1046.58
   140.5 1033.85   157.7 1023.71   169.3 1015.22   178.6 1011.57   199.6 1008.26
   218.7 1006.24   222.8 1006.76   225.3 1008.12   229.9 1010.96   232.2 1011.68
   299.7 1012.65   325.7 1013.77   334.8 1014.66   341.8  1015.9   356.6 1021.18
   367.8 1026.75   376.7 1029.98   388.4  1036.6     408 1048.88     418 1054.14
#Mann= 3, -1 ,  0
       0     0.1       0   199.6   0.045       0   225.3     0.1       0
Bank Sta=199.6,225.3
XS Rating Curve= 0 ,0
Exp/Cntr(USF)=0,0
Exp/Cntr=0.3,0.1

Type RM Length L Ch R = 1 ,6300    ,303.5,300,298
XS GIS Cut Line= 6
1673139.75168543521048.3010487561673199.87951793521111.946262673
1673253.30624834521164.582640335  1673324.541014521234.764914677
1673377.96741635521287.4019485121673440.29800034521348.811602592
#Sta/Elev= 30
       0 1094.77     6.8 1092.23    15.8 1086.75    28.3 1079.92      51 1069.18
    79.7 1061.88   102.5 1053.22   107.6 1051.96   139.4  1041.6   162.9 1030.85
   167.5 1027.53   176.8 1019.26   190.5 1009.18   197.7 1007.19  203.051005.082
   204.9  1004.5   209.3 1004.29  221.491005.081   239.4 1008.36   269.6 1008.25
   290.5 1009.08   327.6 1008.78   355.4 1011.37   362.4 1013.76   374.8 1020.45
   385.6 1026.84   397.8 1035.16   405.9 1039.95   415.7 1044.91   425.1 1048.73
#Mann= 3, -1 ,  0
       0     0.1       0  203.05   0.045       0  221.49     0.1       0
Bank Sta=203.05,221.49
XS Rating Curve= 0 ,0
Exp/Cntr(USF)=0,0
Exp/Cntr=0.3,0.1

Type RM Length L Ch R = 1 ,6000    ,237.5,241.8,243.7
XS GIS Cut Line= 6
1672907.07957859521276.7435052541672972.42885734521338.972055346
1673034.43102993521381.9519562571673122.29338701521429.703501165
1673188.19023684521465.5167497551673265.06934817521507.300130755
#Sta/Elev= 30
       0  1078.5    16.3 1067.29    40.5 1053.57    90.2 1029.61   112.8 1019.81
   124.6 1017.22     191 1013.82   194.8 1011.77  203.16 1003.15   205.8 1001.97
   209.7 1001.74   217.9 1001.86   222.7 1003.18   228.4 1006.56   232.1 1007.71
   239.6 1004.98   250.8  996.51   254.5  994.92     288  993.97     334  994.33
   338.9  996.44   349.8  1005.9   358.2 1011.26   362.8 1011.85   370.3 1011.13
   388.9  1013.9   392.7  1015.6   400.1 1021.34   418.5 1039.75   428.2 1047.87
#Mann= 3, -1 ,  0
       0     0.1       0  203.16   0.045       0   222.7     0.1       0
#XS Ineff= 2 , 0
                          232.85         1015.34
Permanent Ineff=
       F       F
Bank Sta=203.16,222.7
XS Rating Curve= 0 ,0
Exp/Cntr(USF)=0,0
Exp/Cntr=0.3,0.1

Type RM Length L Ch R = 1 ,5758    ,56.2,55.3,53.7
XS GIS Cut Line= 2
1672733.49648906521410.7930403191673058.01737092521684.970587288
#Sta/Elev= 30
       0 1086.39    23.7  1075.4    62.3 1054.59    87.4 1044.19   101.7 1034.88
   109.6 1030.46   126.8 1023.27   148.2 1013.31   164.2  1007.1   172.9 1002.58
     178 1001.65   187.5 1001.37   193.2  998.55   196.8  997.57   210.7  997.58
   220.1  998.99   229.8  997.71     239  994.02   250.3  992.88   310.2  993.02
   315.5  995.11   320.3  998.85   324.8 1001.24   340.7 1003.37   358.7 1011.74
   367.3 1018.49   378.4 1028.54   386.4 1034.43   405.9 1046.81   424.8  1056.2
#Mann= 3, -1 ,  0
       0     0.1       0   196.8   0.045       0   210.7     0.1       0
#XS Ineff= 2 , 0
                           219.9         1018.07
Permanent Ineff=
       F       F
Bank Sta=196.8,210.7
XS Rating Curve= 0 ,0
Exp/Cntr(USF)=0,0
Exp/Cntr=0.3,0.1

Type RM Length L Ch R = 1 ,5703    ,296.7,302.8,307.9
XS GIS Cut Line= 6
1672685.23815876521454.4157220871672752.86564818521512.383781999
1672813.08403167521560.0992377551672900.92243868521610.369806498
1672964.95216626521649.7375099211673031.11968485521708.838441595
#Sta/Elev= 30
       0 1083.34    13.7  1077.3    32.4 1067.58    52.8 1058.12    67.3 1050.24
    83.1 1043.01   106.9 1028.98   116.3 1025.98   125.6 1020.92     146 1012.65
   167.7 1005.29   177.3 1003.17   201.4 1000.21   204.7   998.2   208.8  992.81
   210.8991.3191   215.8   990.4  225.76 991.318   234.9  996.24   238.7  996.54
     250  992.99   311.6  992.87   318.8  993.81   325.9  998.33   330.6 1000.35
   343.2 1001.35   358.9 1008.08   399.3 1038.63     410 1044.36     431 1053.32
#Mann= 3, -1 ,  0
       0     0.1       0   210.8   0.045       0  225.76     0.1       0
#XS Ineff= 2 , 0
                          238.99         1002.29
Permanent Ineff=
       F       F
Bank Sta=210.8,225.76
XS Rating Curve= 0 ,0
Exp/Cntr(USF)=0,0
Exp/Cntr=0.3,0.1

Type RM Length L Ch R = 1 ,5400    ,304.8,300,296.5
XS GIS Cut Line= 6
1672535.89265692521577.5020900821672571.41784833521657.476339594
  1672601.790491521726.0510055871672642.28778534521817.483893588
  1672672.660428521886.0585595821672708.14854601521966.028872088
#Sta/Elev= 30
       0 1065.82    37.1 1049.46    47.4 1047.33    64.5 1040.47    72.5 1036.73
    84.4 1033.61    90.5  1030.6   101.2 1023.73   111.1  1019.2   137.1 1010.16
     155 1007.28   165.8 1003.55   169.4 1001.95     173  999.63   190.9  985.61
  199.39983.6344     216  982.31  220.82983.6356   223.2  984.71   230.4  985.31
   240.7  989.97   248.3  991.11   310.7  992.38   348.8  994.79   352.4  996.04
   363.2 1003.22   385.3 1010.51   395.5 1015.05   402.7 1019.44     425  1035.9
#Mann= 3, -1 ,  0
       0     0.1       0  199.39   0.045       0  220.82     0.1       0
Bank Sta=199.39,220.82
XS Rating Curve= 0 ,0
Exp/Cntr(USF)=0,0
Exp/Cntr=0.3,0.1

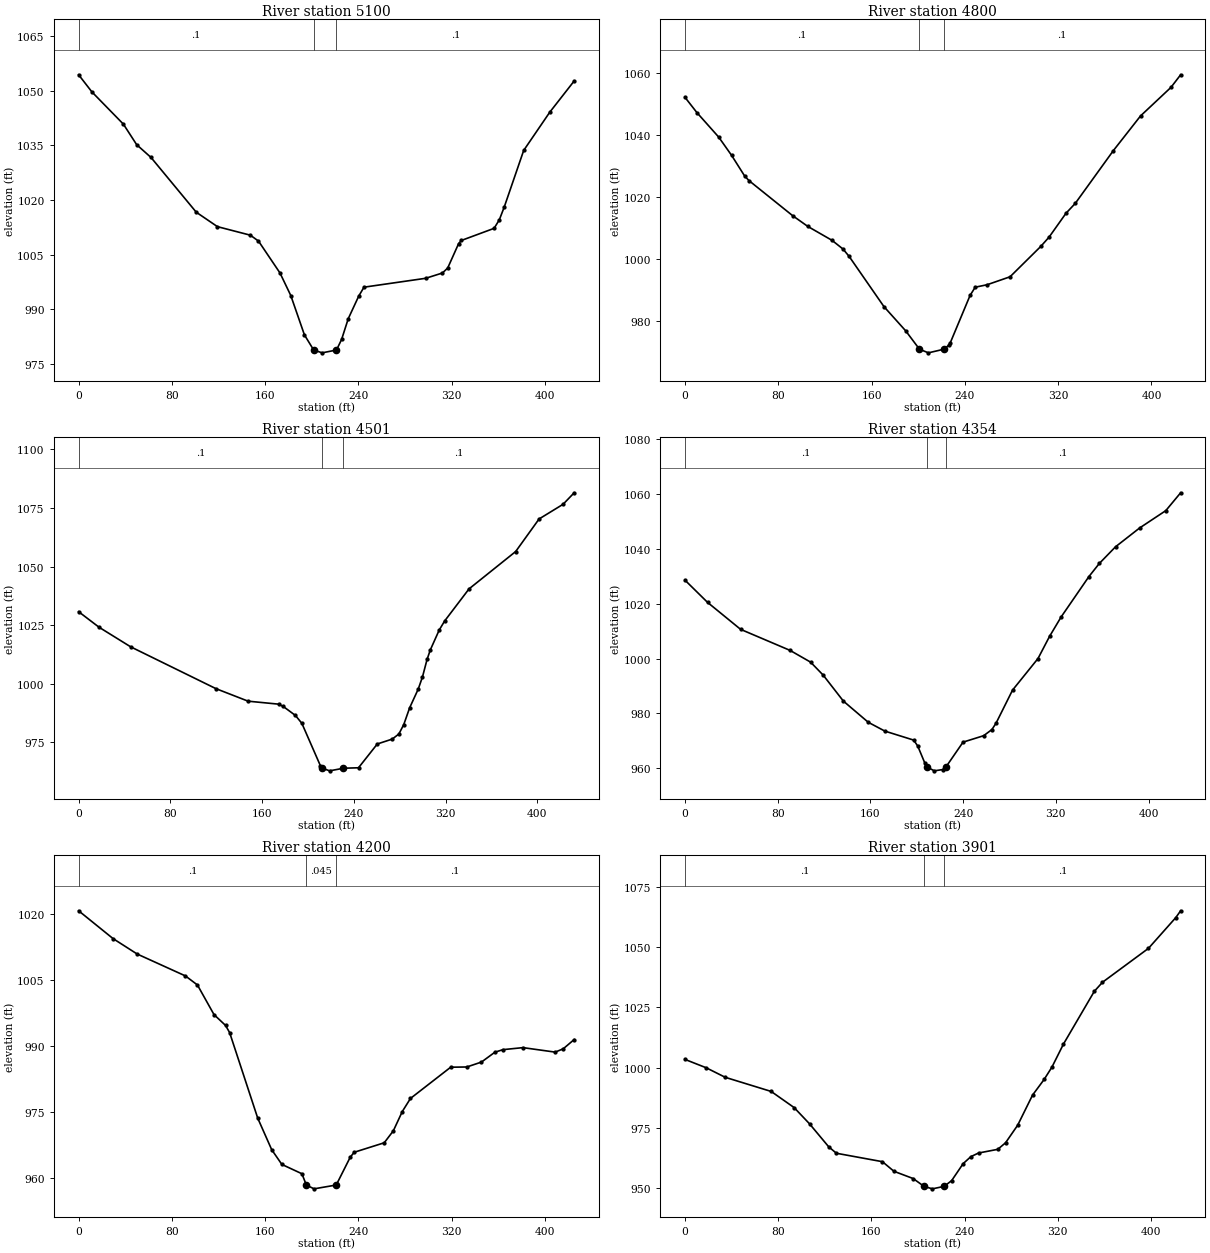
Type RM Length L Ch R = 1 ,5100    ,296.2,300,302.7
XS GIS Cut Line= 6
1672224.86440758521798.2582102571672288.83179934521857.960846752
1672343.66108601521909.1349570011672416.76625475521977.366775915
1672471.59586951522028.5402300061672537.63182667522086.026663587
#Sta/Elev= 30
       0 1054.39    11.4 1049.68    38.4 1040.83    49.8 1035.19    62.1 1031.68
   100.9 1016.65   119.1 1012.68   147.3 1010.34   154.3 1008.72   172.7  999.98
     182  993.77   193.7  982.96  201.64978.8055   208.9  978.03  221.21 978.806
   225.6  981.71   231.3  987.41   240.3  993.62   244.8  996.06   297.7   998.5
   312.1  999.96   316.6 1001.32     326 1008.04   328.4  1008.9   356.4 1012.22
   360.9 1014.57   365.1 1018.06   381.8 1033.62   404.2 1044.13   425.1 1052.69
#Mann= 3, -1 ,  0
       0     0.1       0  201.64   0.045       0  221.21     0.1       0
Bank Sta=201.64,221.21
XS Rating Curve= 0 ,0
Exp/Cntr(USF)=0,0
Exp/Cntr=0.3,0.1

Type RM Length L Ch R = 1 ,4800    ,301.3,299.5,298
XS GIS Cut Line= 6
1672042.02979951521930.1470540911672083.66423067522007.107202008
1672119.35018292522073.0729493351672166.93178068522161.027497843
1672202.61838908 522226.993245171672244.25282025522303.953065008
#Sta/Elev= 30
       0 1052.05    10.1 1047.18    28.8 1039.28    39.9 1033.37    51.1 1026.71
    54.9 1025.21    92.2 1013.95   105.3 1010.46     126 1005.99   135.5 1003.16
   140.7  1000.8   170.5  984.64   189.2  976.81  201.03 970.878   208.7  969.72
  221.85970.8792   226.5  972.28   227.5  973.02   244.4  988.22   248.8  990.88
     259  991.67   278.7  994.24     305 1004.01   312.2 1007.04   326.7 1014.73
   334.6 1017.89   367.3 1034.92   390.6 1046.09   416.7  1055.3     425 1059.36
#Mann= 3, -1 ,  0
       0     0.1       0  201.03   0.045       0  221.85     0.1       0
Bank Sta=201.03,221.85
XS Rating Curve= 0 ,0
Exp/Cntr(USF)=0,0
Exp/Cntr=0.3,0.1

Type RM Length L Ch R = 1 ,4501    ,144.2,146,148.2
XS GIS Cut Line= 6
1671798.05915885522149.239463672 1671861.5993861522215.844973505
 1671910.2190395522276.3829101771671968.52961843522357.628810674
   1672012.88222522418.109004676 1672064.6265391522488.669559091
#Sta/Elev= 30
       0 1030.71    17.8 1024.08    45.4 1015.71   119.8  997.85   147.8  992.51
   174.4  991.24   178.5  990.24   189.1  986.41   194.7  983.05   210.8  965.02
   212.6963.8931   218.9  962.77     231  963.88   244.1  964.08   260.5  974.24
   273.5  976.32   279.3  978.49   283.6  982.55   288.7  989.68   296.2  997.68
   299.9 1002.87   303.9 1010.34   306.7 1014.36   314.5 1022.89   319.2 1026.73
   340.5 1040.45   381.2 1056.41   401.6  1070.3   422.5 1076.56   432.2 1081.48
#Mann= 3, -1 ,  0
       0     0.1       0   212.6   0.045       0     231     0.1       0
Bank Sta=212.6,231
XS Rating Curve= 0 ,0
Exp/Cntr(USF)=0,0
Exp/Cntr=0.3,0.1

Type RM Length L Ch R = 1 ,4354    ,154.8,154.5,155.1
XS GIS Cut Line= 2
1671724.59652532522180.3112636291671889.78580821522574.804391258
#Sta/Elev= 30
       0 1028.55    19.4 1020.48    47.9 1010.65    90.6 1002.97   108.3  998.69
   119.2  993.94   136.6  984.48   158.1  976.74   172.4  973.53   197.3  970.24
   200.8  968.07   206.8  961.98  209.06960.4149     215  959.03   222.2  959.48
   225.1960.4157   239.9   969.5   257.7  971.85   264.8  974.09   268.4  976.43
   282.6  988.47   304.6 1000.01   314.6 1008.11   324.6  1015.2   348.5 1029.88
   357.5 1034.68   371.5 1040.76   392.3 1047.63   414.9 1053.96   427.7 1060.47
#Mann= 3, -1 ,  0
       0     0.1       0  209.06   0.045       0   225.1     0.1       0
Bank Sta=209.06,225.1
XS Rating Curve= 0 ,0
Exp/Cntr(USF)=0,0
Exp/Cntr=0.3,0.1

Type RM Length L Ch R = 1 ,4200    ,296.7,298.8,300.6
XS GIS Cut Line= 6
1671593.52282251522216.0683982521671620.38530159522299.342838004
1671643.41084608522370.7213041781671674.11124401522465.892045587
1671697.13580425522537.2701836681671723.99893951 522620.54462342
#Sta/Elev= 30
       0 1020.76    29.5 1014.44    50.2 1010.93    91.6 1005.95   101.9 1003.89
   116.1  997.16     126   994.7   129.5  993.07   153.6  973.62   165.6  966.44
   174.3   963.1   191.5  960.98  195.29958.4175   201.9  957.55  220.93 958.419
   232.9  964.72   236.3  965.86   262.1  968.02   269.9  970.74   277.6  975.13
   284.6   978.1   319.1   985.2   332.9  985.25   345.5  986.37     357  988.61
   363.9  989.19   381.1  989.65   408.7  988.63   415.6  989.38     425  991.49
#Mann= 3, -1 ,  0
       0     0.1       0  195.29   0.045       0  220.93     0.1       0
Bank Sta=195.29,220.93
XS Rating Curve= 0 ,0
Exp/Cntr(USF)=0,0
Exp/Cntr=0.3,0.1

Type RM Length L Ch R = 1 ,3901    ,312.5,301.5,286.7
XS GIS Cut Line= 6
1671354.51312992522275.3179516791671359.12434117522362.741989419
1671365.48423658522437.4714987581671376.41630134522536.902730346
1671387.33917975522611.244445175 1671400.3775395522697.950964674
#Sta/Elev= 30
       0 1003.36    18.1  999.91    34.5  995.94    73.9  990.08    93.6  983.38
   106.8  976.65   123.3  967.09   129.9  964.42   169.4  960.92   179.3  956.93
   195.8  953.92  205.11950.6715   212.3  949.65  222.34950.6731   228.8  953.05
   238.7  960.11   245.3  963.01   251.9  964.52   268.4  966.05   275.1  968.77
   285.5  976.06   298.3  988.58   308.2  995.05   314.9 1000.17   324.8 1009.74
   351.3 1031.65   358.3  1035.4   397.8 1049.49   421.2 1062.23   425.4 1065.08
#Mann= 3, -1 ,  0
       0     0.1       0  205.11   0.045       0  222.34     0.1       0
Bank Sta=205.11,222.34
XS Rating Curve= 0 ,0
Exp/Cntr(USF)=0,0
Exp/Cntr=0.3,0.1

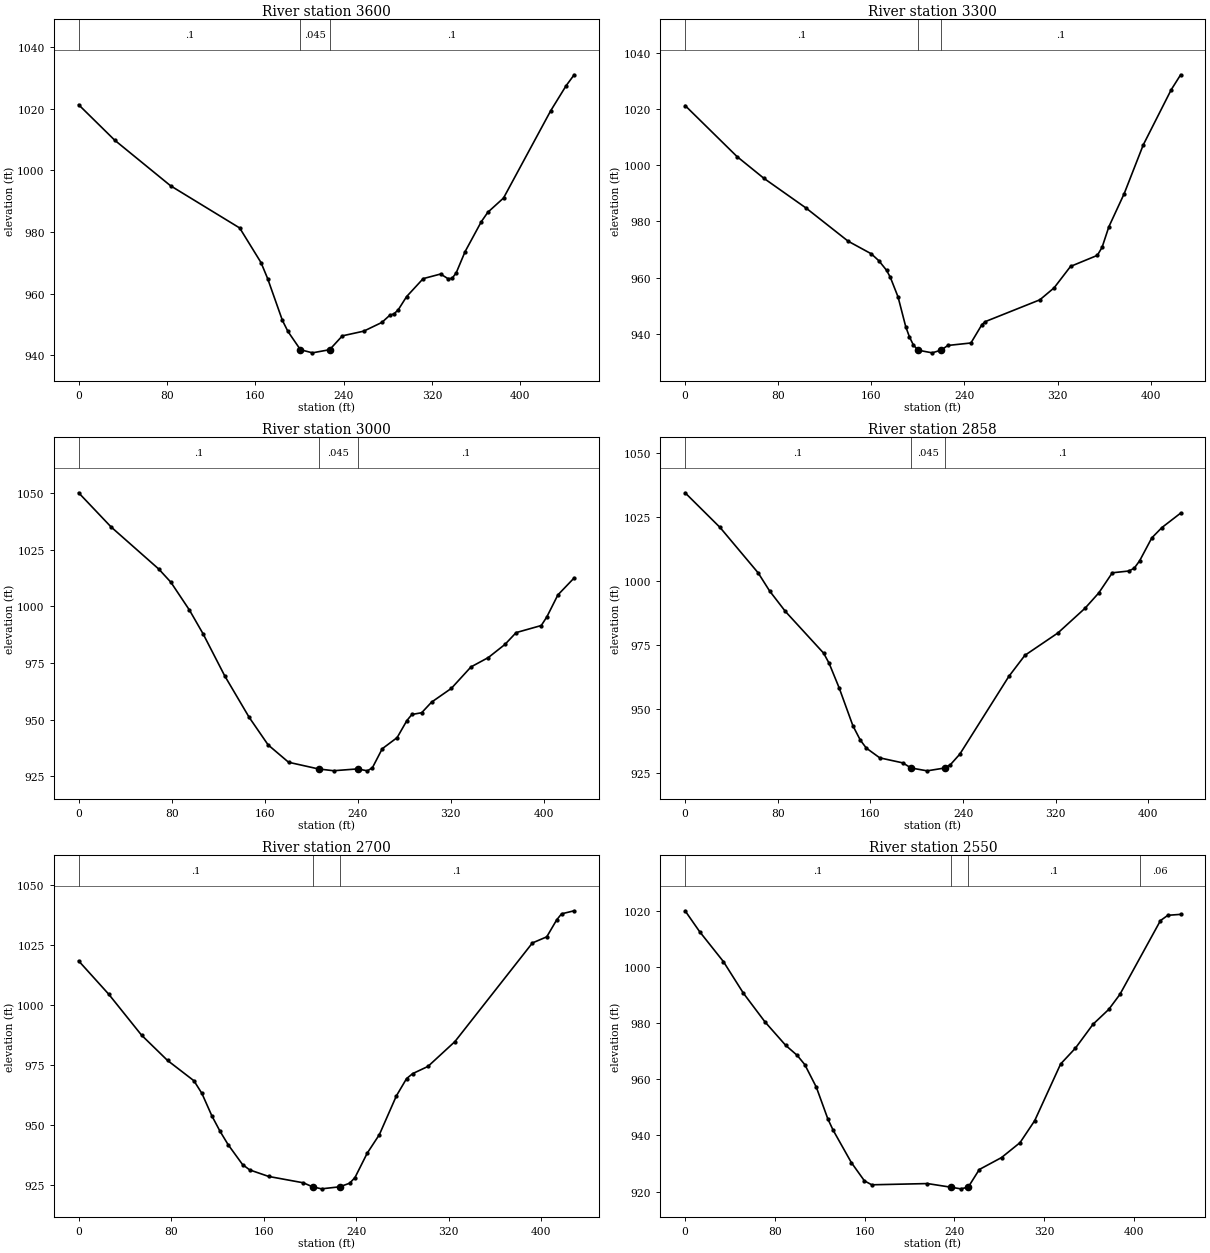
Type RM Length L Ch R = 1 ,3600    ,284.8,299.4,310.7
XS GIS Cut Line= 6
1670932.42079826522379.2242399161670996.88425201522439.923593596
1671060.51962343522479.5478581791671145.09327318522532.944076836
1671186.48032951522608.5466159281671224.06785275522700.386327252
#Sta/Elev= 30
       0 1021.35    32.7 1009.82    83.3  995.01   145.9   981.3   165.2  970.07
   171.2  964.88   184.6  951.27   189.6  947.68  200.92941.7516   211.8  940.73
  227.38941.7521   238.9  946.25   258.3  947.78   274.7  950.61   281.7  952.89
   285.9  953.45   289.6  954.76   297.1     959   312.1  964.84   327.9  966.34
   334.5  964.85   338.2   964.9     342  966.69   350.1  973.63   364.8  983.36
   370.7  986.41   384.9  991.03   427.6 1019.37   441.6 1027.53   448.9 1031.08
#Mann= 3, -1 ,  0
       0     0.1       0  200.92   0.045       0  227.38     0.1       0
Bank Sta=200.92,227.38
XS Rating Curve= 0 ,0
Exp/Cntr(USF)=0,0
Exp/Cntr=0.3,0.1

Type RM Length L Ch R = 1 ,3300    ,306.1,300.2,283
XS GIS Cut Line= 6
1670866.13188884522406.1434774251670864.30643317522493.762068585
1670856.95835076522568.3701870891670847.64045601522668.075368255
1670841.29335584522743.0519243331670833.98169068522830.540266424
#Sta/Elev= 30
       0 1021.25    44.6 1003.08    67.7  995.33   103.9  984.75   140.1  972.93
   159.9  968.46   166.5  965.97   173.1  962.58   176.4  960.02     183  953.06
   189.6  942.46   192.8  938.82   196.1  936.01  200.07934.1251   212.3  933.17
  219.87934.1246   225.8   935.8   245.6  936.68   255.1  943.26   258.1  944.32
   304.8  952.05   317.1  956.33   331.2  963.95   354.2  967.88   358.3  970.75
   364.1  978.05   377.3  989.87   393.7 1007.25   417.7 1026.88   425.8  1032.2
#Mann= 3, -1 ,  0
       0     0.1       0  200.07   0.045       0  219.87     0.1       0
Bank Sta=200.07,219.87
XS Rating Curve= 0 ,0
Exp/Cntr(USF)=0,0
Exp/Cntr=0.3,0.1

Type RM Length L Ch R = 1 ,3000    ,143.2,141.7,140.1
XS GIS Cut Line= 6
1670431.06484559522491.5885165041670486.47287126522559.310165837
 1670533.9658865 522617.356965751670597.28892259522694.753136426
1670644.78193784 522752.799608261670689.82253018522828.976621255
#Sta/Elev= 30
       0 1050.02    27.9 1034.95    68.9 1016.38    79.3 1010.57    95.3  998.26
     107  987.81   125.6  969.27   146.6     951   162.9  938.84   180.5  931.18
  206.22928.2333   219.2  927.45   239.8  928.25   248.3   927.4   252.6  928.82
     261  937.14   273.8  942.05   282.2  949.58   286.5  952.26   294.9  953.02
   303.4  957.69   320.4  963.76   337.3  973.23   352.2  977.36   366.5  983.15
   376.1  988.36   397.7  991.48   402.5  995.28     412 1004.98     426 1012.48
#Mann= 3, -1 ,  0
       0     0.1       0  206.22   0.045       0   239.8     0.1       0
Bank Sta=206.22,239.8
XS Rating Curve= 0 ,0
Exp/Cntr(USF)=0,0
Exp/Cntr=0.3,0.1

Type RM Length L Ch R = 1 ,2858    ,156.5,158.3,160
XS GIS Cut Line= 2
1670307.21213502522600.4166920451670613.95631329522898.779881839
#Sta/Elev= 30
       0 1034.42    30.2 1020.89    63.1 1003.18      73  996.12    86.6  988.15
   119.6  971.89   124.3  967.99     133  958.38   144.9  943.57   151.3  937.97
   156.5  934.85   168.1  931.05   187.9   929.1  195.21927.0936     209  925.99
  224.14927.0937   229.1   928.4   237.2  932.49   279.5  962.78   293.4  971.03
   321.9  979.75   345.4  989.42   357.2  995.36   368.9 1003.22   383.1 1003.91
   387.8 1004.99   392.5 1007.91     403 1016.83   411.7 1020.85   427.9 1026.49
#Mann= 3, -1 ,  0
       0     0.1       0  195.21   0.045       0  224.14     0.1       0
Bank Sta=195.21,224.14
XS Rating Curve= 0 ,0
Exp/Cntr(USF)=0,0
Exp/Cntr=0.3,0.1

Type RM Length L Ch R = 1 ,2700    ,144.1,150,153.5
XS GIS Cut Line= 6
1670227.31820583522669.6954437491670262.52253176522753.527297094
1670309.37480025522812.0921405851670371.84449159522890.178926677
1670418.69676009522948.7440982611670473.35806809523017.069749013
#Sta/Elev= 30
       0 1018.38      26 1004.51    54.4  987.44    76.9  976.89    99.7  968.44
   106.6  963.15   115.2  953.81   122.2  947.45   129.2  941.86   141.7  933.55
   147.9  931.31   164.3  928.59   194.3  925.94  202.21924.2768     210  923.43
  225.68924.2775   234.3  925.77   238.9  928.13   249.5   938.3     260  946.02
   274.7  962.15   283.5  969.35   288.8  971.43     302  974.42   325.3  984.76
   392.3 1025.85   404.7  1028.4   413.3 1035.47   417.5 1037.98   428.4 1039.25
#Mann= 3, -1 ,  0
       0     0.1       0  202.21   0.045       0  225.68     0.1       0
Bank Sta=202.21,225.68
XS Rating Curve= 0 ,0
Exp/Cntr(USF)=0,0
Exp/Cntr=0.3,0.1

Type RM Length L Ch R = 1 ,2550    ,158.4,155.7,146.1
XS GIS Cut Line= 3
1670154.12732508522696.1785830011670214.78925492522903.046521588
1670237.11361012523128.113525225
#Sta/Elev= 30
       0 1020.13      13 1012.66    34.2 1001.99      52  990.73    71.2  980.52
    89.7  972.14    99.9  968.59   106.7  965.29     117  957.23   127.3  945.88
     132  941.88   148.2  930.36   159.9  923.82   166.4  922.42   216.1  922.86
  236.83  921.57   245.8  920.98   252.4  921.58   262.3  927.87   282.1  932.13
   298.6  937.45   311.7   945.3   334.8   965.5     348  971.15   363.7  979.67
   377.7  984.96   387.6  990.28   423.8 1016.63   430.4 1018.52   441.8 1018.85
#Mann= 4, -1 ,  0
       0     0.1       0  236.83   0.045       0   252.4     0.1       0
  405.58    0.06       0
Bank Sta=236.83,252.4
XS Rating Curve= 0 ,0
Exp/Cntr(USF)=0,0
Exp/Cntr=0.3,0.1