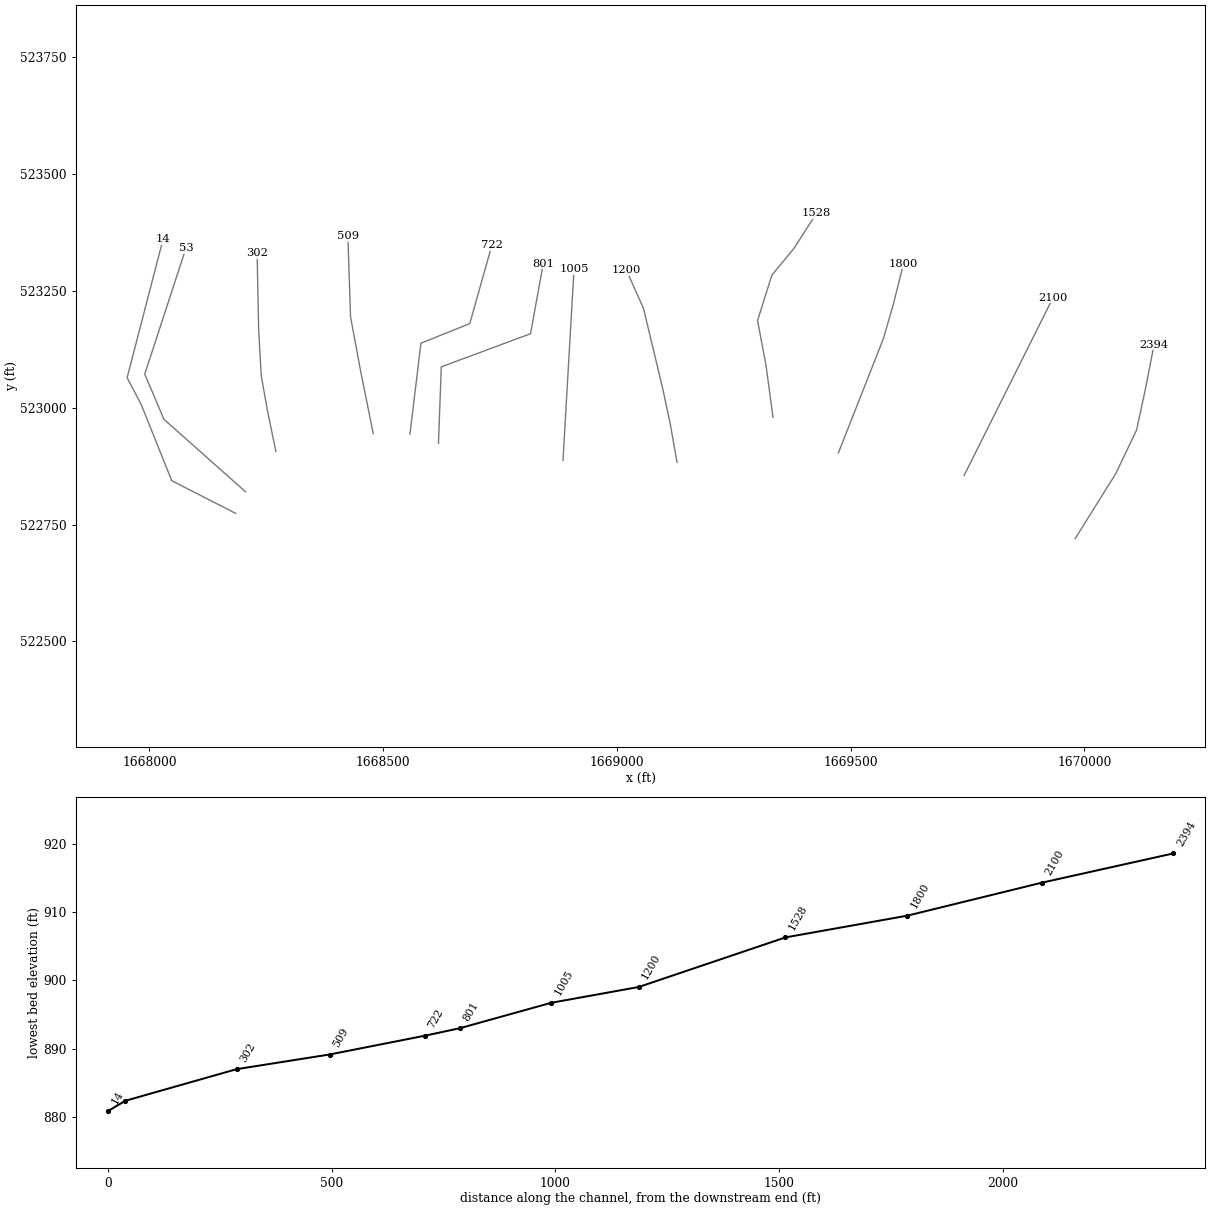
HEC-RAS study GrannyRn.prj: GrannyRn

--- GrannyRn.g01 (geometry) --- (continued)

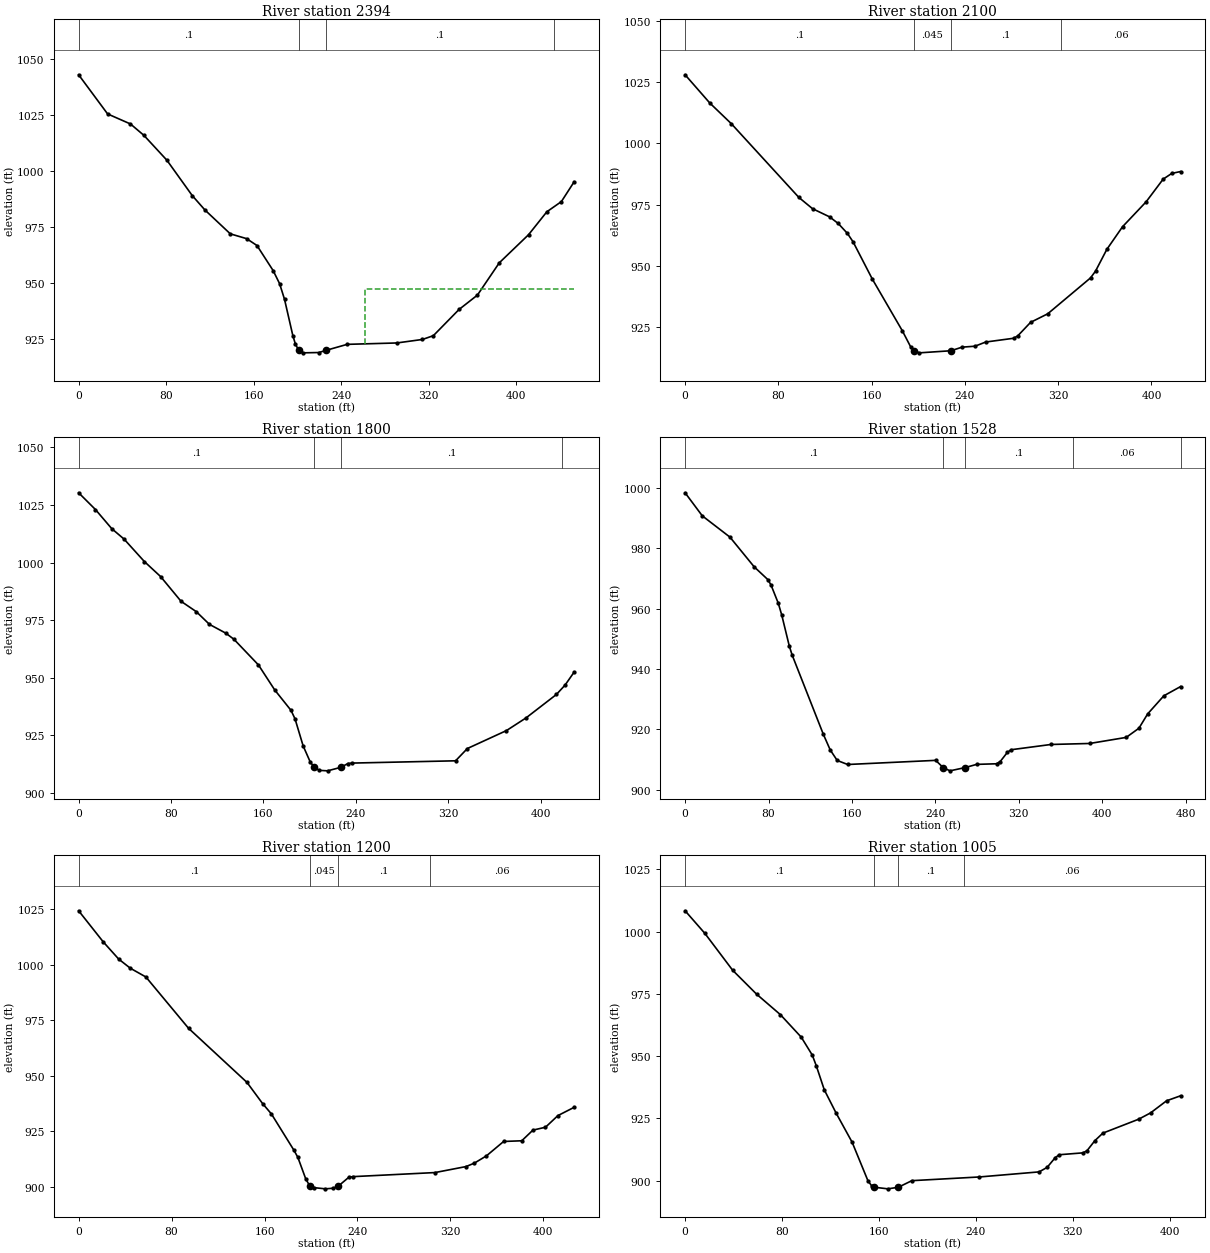
Type RM Length L Ch R = 1 ,2394    ,294,294.4,293.5
XS GIS Cut Line= 6
1669980.45682292522720.3321534991670026.83271442522794.531480178
1670066.58197875522858.1320747581670111.53726943522952.072503671
1670130.19372818523038.6202308391670148.96698458523134.874631509
#Sta/Elev= 30
       0 1043.12    26.5 1025.59    47.4  1021.1    59.7    1016    80.7 1004.88
   103.9  989.04   115.5  982.59   138.7  971.91   153.6  969.76   163.1  966.68
   177.9  955.45   183.8   949.6   188.3  942.59   195.9  926.36   198.3  922.47
  201.38919.7204   205.6  918.63   219.7  918.77   226.1  919.72   245.6  922.43
   290.9  923.05   314.4  924.62   324.4  926.31   347.9  938.04   364.7  944.47
   384.7  958.93   411.5  971.53   428.2  981.78   441.5  986.34   453.2  995.23
#Mann= 4, -1 ,  0
       0     0.1       0  201.38   0.045       0   226.1     0.1       0
  435.18    0.06       0
#XS Ineff= 2 , 0
                          262.01          947.11
Permanent Ineff=
       F       F
Bank Sta=201.38,226.1
XS Rating Curve= 0 ,0
Exp/Cntr(USF)=0,0
Exp/Cntr=0.3,0.1

Type RM Length L Ch R = 1 ,2100    ,296.1,300,300.7
XS GIS Cut Line= 6
1669742.61773168 522855.08089976  1669781.748887522933.343210429
1669815.28983042523000.4250972571669860.01152575523089.867831752
1669893.55246918523156.9497185951669932.68395258523235.212029248
#Sta/Elev= 30
       0 1028.09    21.2 1016.53    39.6  1008.1    97.6   977.9   109.3   973.3
   123.9  969.97   131.3  967.26   139.2   963.2   144.1  959.72   160.6  944.48
   186.3  923.36   193.6  916.65  196.23915.1831     201  914.33  227.95915.1854
   237.6  916.66   248.6  917.04   257.8  918.75   281.7  920.29   285.3  921.27
   296.3   926.8     311   930.3   347.7  944.98     352  947.76   361.7  956.66
   375.2  965.94   395.4  976.12     410  985.39   417.4  987.74     425  988.51
#Mann= 4, -1 ,  0
       0     0.1       0  196.23   0.045       0  227.95     0.1       0
   322.5    0.06       0
Bank Sta=196.23,227.95
XS Rating Curve= 0 ,0
Exp/Cntr(USF)=0,0
Exp/Cntr=0.3,0.1

Type RM Length L Ch R = 1 ,1800    ,271.4,272.3,272.4
XS GIS Cut Line= 6
1669473.61892584522903.1280477491669505.68972784522984.538974166
1669533.17917417523054.3193464281669569.83231609523147.360170841
1669590.98319243523220.3190144151669613.07829259523308.205321595
#Sta/Elev= 30
       0  1030.3    14.6    1023    28.7  1014.7    39.3  1010.2    56.9 1000.44
      71  993.89    88.7  983.15   101.9  978.65   113.3  973.12   127.4  969.32
   134.5  966.65   155.7  955.51   169.8  944.64   183.9  935.78   187.4  932.06
   194.4  920.35   200.5  913.41  203.99911.0237   208.5  909.71   215.6   909.5
  226.97 911.022   233.2  912.68   236.8  912.87   326.4  913.86   336.6  919.19
   370.5     927   387.4  932.49   413.7  942.67   421.2  946.74   429.1  952.42
#Mann= 4, -1 ,  0
       0     0.1       0  203.99   0.045       0  226.97     0.1       0
  418.46    0.06       0
Bank Sta=203.99,226.97
XS Rating Curve= 0 ,0
Exp/Cntr(USF)=0,0
Exp/Cntr=0.3,0.1

Type RM Length L Ch R = 1 ,1528    ,323.3,327.7,331.6
XS GIS Cut Line= 6
1669333.84459908522979.0773709271669318.92894651523089.976755425
1669300.79414026523186.4745939231669331.31474851523283.404190093
1669379.15750059523341.4778928461669426.73647368523415.811077505
#Sta/Elev= 30
       0  998.37    16.5  990.73      43  983.69    66.2  973.87    79.4  969.61
    82.4  967.83    89.4  961.77    92.7  957.87    99.9  947.66   102.6   944.7
   132.6  918.38   139.2  913.21   145.9  909.74   155.9  908.41   240.3  909.78
  247.43907.4127     254  906.31  268.78 907.412   279.6  908.45   298.7  908.65
   302.2  909.39   309.1  912.45   312.7   913.3   350.9  915.04     388  915.37
     423  917.38   435.2  920.41   443.6  925.17   459.1  931.15   475.2  934.22
#Mann= 5, -1 ,  0
       0     0.1       0  247.43   0.045       0  268.78     0.1       0
  371.71    0.06       0  475.21     0.1       0
Bank Sta=247.43,268.78
XS Rating Curve= 0 ,0
Exp/Cntr(USF)=0,0
Exp/Cntr=0.3,0.1

Type RM Length L Ch R = 1 ,1200    ,199.2,195.6,193.3
XS GIS Cut Line= 6
1669128.55924851522882.7068287581669113.30370159522969.046551093
1669097.52847068523042.3902364221669074.19091892523139.628887087
1669056.68832925523212.557875082  1669020.455134523293.677463502
#Sta/Elev= 30
       0 1024.28    21.2 1010.26    34.5 1002.51    44.5   998.4    57.9  994.46
    94.6  971.36   144.9  946.98   158.3  937.47   165.9  932.79   185.3  916.43
   188.7   913.2   195.4  903.62   198.8  900.44  199.55  900.25   202.2   899.6
   212.3  899.04     219  899.31  223.45900.2508   232.5  904.23   235.9  904.53
   306.7  906.37   333.5  909.08   340.7  910.65     351   913.9   365.8  920.38
   381.4  920.69     391  925.49   401.8  926.78   412.5  932.03   426.5  935.76
#Mann= 4, -1 ,  0
       0     0.1       0  199.55   0.045       0  223.45     0.1       0
   302.7    0.06       0
Bank Sta=199.55,223.45
XS Rating Curve= 0 ,0
Exp/Cntr(USF)=0,0
Exp/Cntr=0.3,0.1

Type RM Length L Ch R = 1 ,1005    ,214.4,203.7,192.2
XS GIS Cut Line= 2
1668884.54914958 522887.346539171668908.15874704523295.792575159
#Sta/Elev= 30
       0 1008.37    16.3  999.31    39.3  984.47      59   974.9    78.7  966.65
    95.9  957.62     105  950.42   108.3  946.14   114.9  936.49   124.7  927.11
   137.9  915.43     151   899.9   154.3  897.76  155.99  897.38   167.4  896.72
     176  897.35   187.2     900     243  901.49   292.3  903.53   298.9  905.35
   305.5   909.2   308.8  910.41   328.5  911.17   331.8  912.03   338.3  916.07
   344.9  919.09   374.5  924.69   384.3  927.22   397.5  932.08   409.1  934.09
#Mann= 4, -1 ,  0
       0     0.1       0  155.99   0.045       0     176     0.1       0
     230    0.06       0
Bank Sta=155.99,176
XS Rating Curve= 0 ,0
Exp/Cntr(USF)=0,0
Exp/Cntr=0.3,0.1

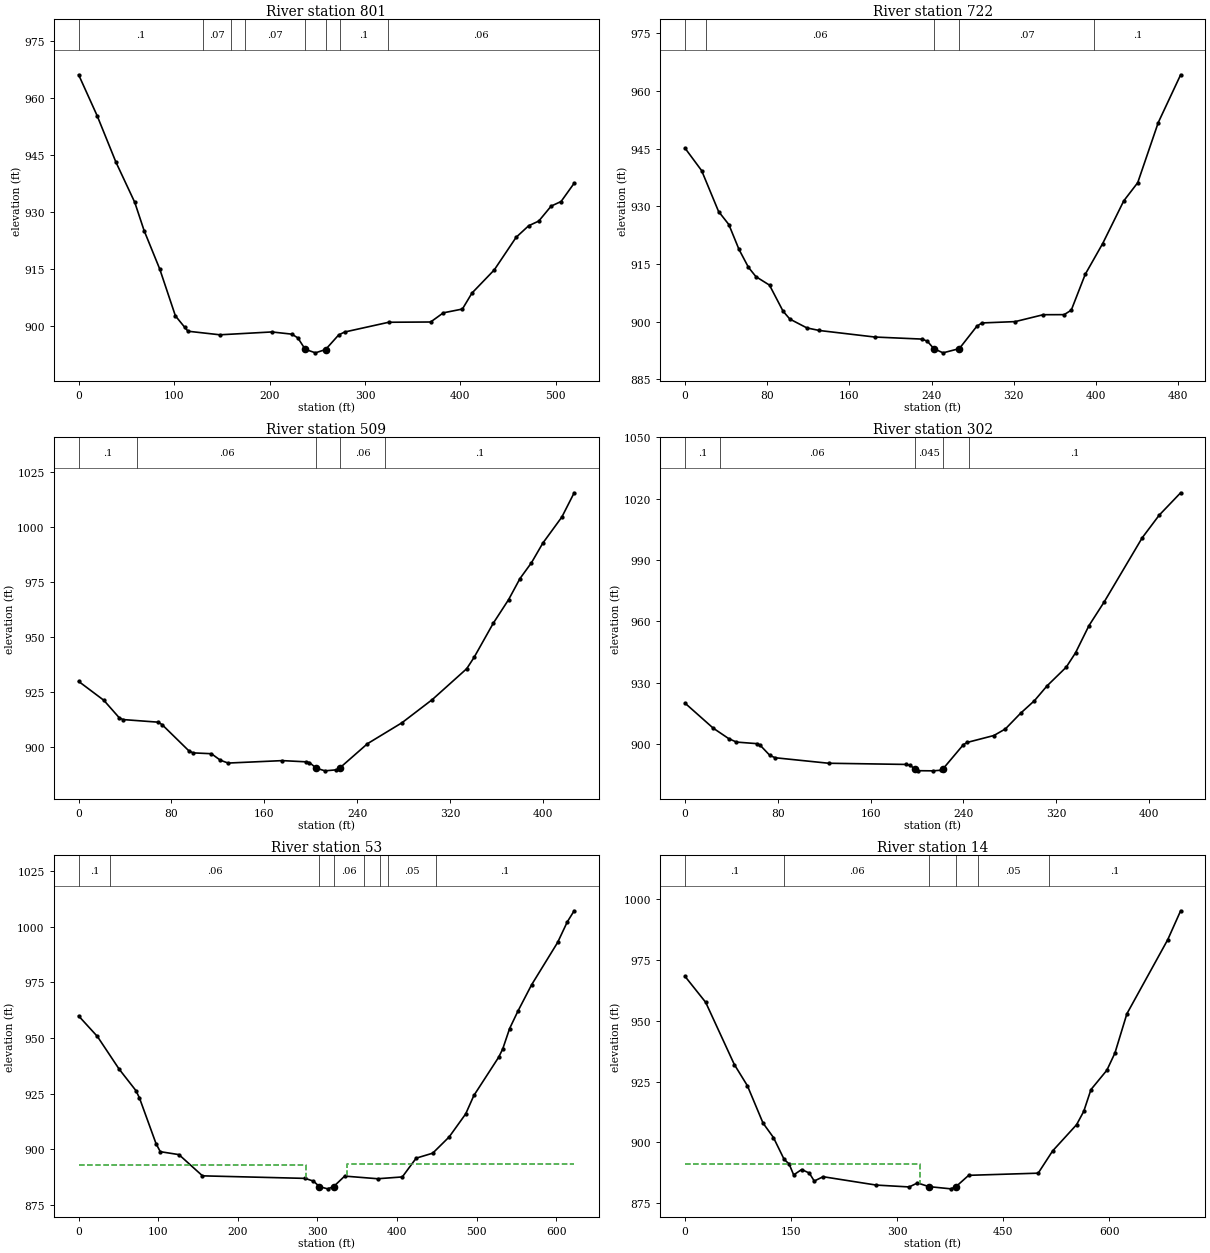
Type RM Length L Ch R = 1 ,801     ,82.1,78.9,80.3
XS GIS Cut Line= 4
1668618.15142767522923.6217306411668624.29162437523087.393744027
 1668815.1533547523158.2145090431668842.23228627523307.527331165
#Sta/Elev= 30
       0   966.2    19.4  955.42    39.1  943.19    58.8  932.62    68.6  925.18
      85  915.05   101.4  902.73   111.3  899.68   114.6  898.69     148  897.75
   202.4   898.5   223.4  897.92   229.7  896.93   237.4  893.93   248.1     893
  258.74  893.87   272.4   897.7   278.7  898.48   324.9  901.05   368.8  901.12
   382.1  903.53   402.1  904.53   412.1  908.73   435.5  914.84   458.4  923.42
   471.5  926.45   482.1  927.69   495.1  931.63   505.5  932.84   519.2  937.66
#Mann= 8, -1 ,  0
       0     0.1       0     130    0.07       0     160    0.06       0
  173.89    0.07       0   237.4   0.045       0  258.74    0.07       0
  273.89     0.1       0  323.89    0.06       0
Bank Sta=237.4,258.74
XS Rating Curve= 0 ,0
Exp/Cntr(USF)=0,0
Exp/Cntr=0.3,0.1

Type RM Length L Ch R = 1 ,722     ,193.9,212.5,222.5
XS GIS Cut Line= 4
1668557.22101813522943.3665437161668580.69692299523137.922846245
1668685.21385072523179.8413883311668732.36815521523347.347517171
#Sta/Elev= 30
       0  945.07    16.1  939.26    32.6  928.63    42.6  925.24    52.5  918.77
    61.7  914.12      69  911.69    82.2  909.49    95.4  902.72     102  900.67
   118.6  898.37   130.7   897.7   184.7     896     231  895.46     236  894.89
   242.2892.9843   251.2  891.89  267.04892.9839     284  898.76     289  899.66
   321.5  900.01   348.8   901.8   369.2  901.82   376.1  902.99   389.7  912.31
   406.7  920.31   427.2  931.39   440.8  936.12   460.8  951.75   482.6  964.17
#Mann= 5, -1 ,  0
       0     0.1       0      20    0.06       0   242.2   0.045       0
  267.04    0.07       0  398.58     0.1       0
Bank Sta=242.2,267.04
XS Rating Curve= 0 ,0
Exp/Cntr(USF)=0,0
Exp/Cntr=0.3,0.1

Type RM Length L Ch R = 1 ,509     ,209.5,207.5,206.4
XS GIS Cut Line= 4
1668478.64606742522944.6831954051668451.32366391523080.196856929
1668430.11222018523194.3601676711668424.41139638523366.877963352
#Sta/Elev= 30
       0  929.83    21.7  921.24    35.1  913.22    38.4  912.46    68.5  911.28
    71.9  910.17    94.9  898.29    98.6  897.31   114.4  896.93   122.1  893.98
   128.8  892.68   175.5  893.79   195.5  893.25   198.9   892.9  204.74890.3836
   212.2  889.14   222.2   889.6  224.89890.3833   248.9  901.49   278.6  911.01
   304.8  921.58   334.4   935.6   340.7   940.7   357.3   956.3   370.5  967.03
   380.3  976.61   390.2  983.81     400  992.74   416.4 1004.61     427 1015.63
#Mann= 5, -1 ,  0
       0     0.1       0      50    0.06       0  204.74   0.045       0
  224.89    0.06       0  264.36     0.1       0
Bank Sta=204.74,224.89
XS Rating Curve= 0 ,0
Exp/Cntr(USF)=0,0
Exp/Cntr=0.3,0.1

Type RM Length L Ch R = 1 ,302     ,243.2,248.7,251.2
XS GIS Cut Line= 6
1668270.42677842522906.1027793441668252.51933393522993.262053832
 1668239.0849776523068.0086235111668233.52199659523167.917216346
 1668232.0219996523242.9019744991668230.27233118523330.384739175
#Sta/Elev= 30
       0  920.03    24.2  907.87    37.6  902.74    44.3  901.04    62.1  900.27
    64.9  899.41    73.2  894.49    77.8  893.38   123.8   890.7   190.8  890.12
   194.1  889.66  198.01888.0417   200.7  887.06   213.8  886.99   220.4  887.28
  222.62888.0413   240.1  899.79   243.4  900.88   266.4  904.25   276.3  907.46
   289.4  915.11   301.4  921.28   312.3  928.53   328.8  937.64   336.8  944.63
   348.4  957.92   361.6  969.56   394.4  1000.9     409  1011.9   427.5 1022.84
#Mann= 5, -1 ,  0
       0     0.1       0      30    0.06       0  198.01   0.045       0
  222.62    0.06       0  244.92     0.1       0
Bank Sta=198.01,222.62
XS Rating Curve= 0 ,0
Exp/Cntr(USF)=0,0
Exp/Cntr=0.3,0.1

Type RM Length L Ch R = 1 ,53      ,34.2,39.1,39.9
XS GIS Cut Line= 4
1668205.62709115522819.9370208611668030.91365296522975.144546473
1667989.91469542523071.8376867341668078.13660155 523341.59444174
#Sta/Elev= 30
       0  959.91    23.6  950.69    50.8  936.09    71.9  926.45    76.3  923.23
    97.3  902.57   102.6  899.02     126   897.7   155.6  888.18   284.5  887.04
     295  885.81   302.5883.3356   312.8  882.35  320.26883.3345   334.2  888.06
   375.7  886.88   406.6  887.69     424  896.11   444.8  898.35   465.5  905.65
   486.2  915.95   496.5  924.22   527.6  941.36   532.7  945.05   541.4  954.25
   551.8  962.04     569  973.87   601.7  992.86   613.9 1002.13   622.5 1007.08
#Mann= 8, -1 ,  0
       0     0.1       0      40    0.06       0   302.5   0.045       0
  320.26    0.06       0  358.72    0.05       0  378.72    0.06       0
  388.72    0.05       0  448.72     0.1       0
#XS Ineff= 2 , 0
          285.05   893.1  337.62          893.49
Permanent Ineff=
       F       F
Bank Sta=302.5,320.26
XS Rating Curve= 0 ,0
Exp/Cntr(USF)=0,0
Exp/Cntr=0.3,0.1

Type RM Length L Ch R = 1 ,14      ,,,
XS GIS Cut Line= 5
1668184.39209787522773.9006081231668047.66839168522843.787292399
1667982.56700005523006.2065229361667952.22195507523064.113286623
 1668029.2443463523360.929739125
#Sta/Elev= 30
       0  968.23    29.1  957.59    69.6  931.99    88.1  923.25   110.2  907.87
   124.9  901.95     140  892.96     147  891.08   153.5  886.56   164.8  888.77
   175.6  887.31   182.6  884.03   195.1  885.81   270.2  882.37   316.9   881.6
   328.5  883.25  344.71881.7303   375.7  880.82  382.87881.6999   400.9  886.38
   499.2  887.27   519.6  896.42   553.5  907.23   563.6  912.71   573.8  921.67
   596.3  929.64   607.7  936.72   624.6  952.87   682.3  983.34   700.6  995.27
#Mann= 6, -1 ,  0
       0     0.1       0     140    0.06       0  344.71   0.045       0
  382.87    0.06       0  413.91    0.05       0  513.91     0.1       0
#XS Ineff= 2 , 0
          332.13  890.89
Permanent Ineff=
       F       F
Bank Sta=344.71,382.87
XS Rating Curve= 0 ,0
Exp/Cntr(USF)=0,0
Exp/Cntr=0.3,0.1
LCMann Table=0

Chan Stop Cuts=-1
Use User Specified Reach Order=0
Composite Channel Slope=5